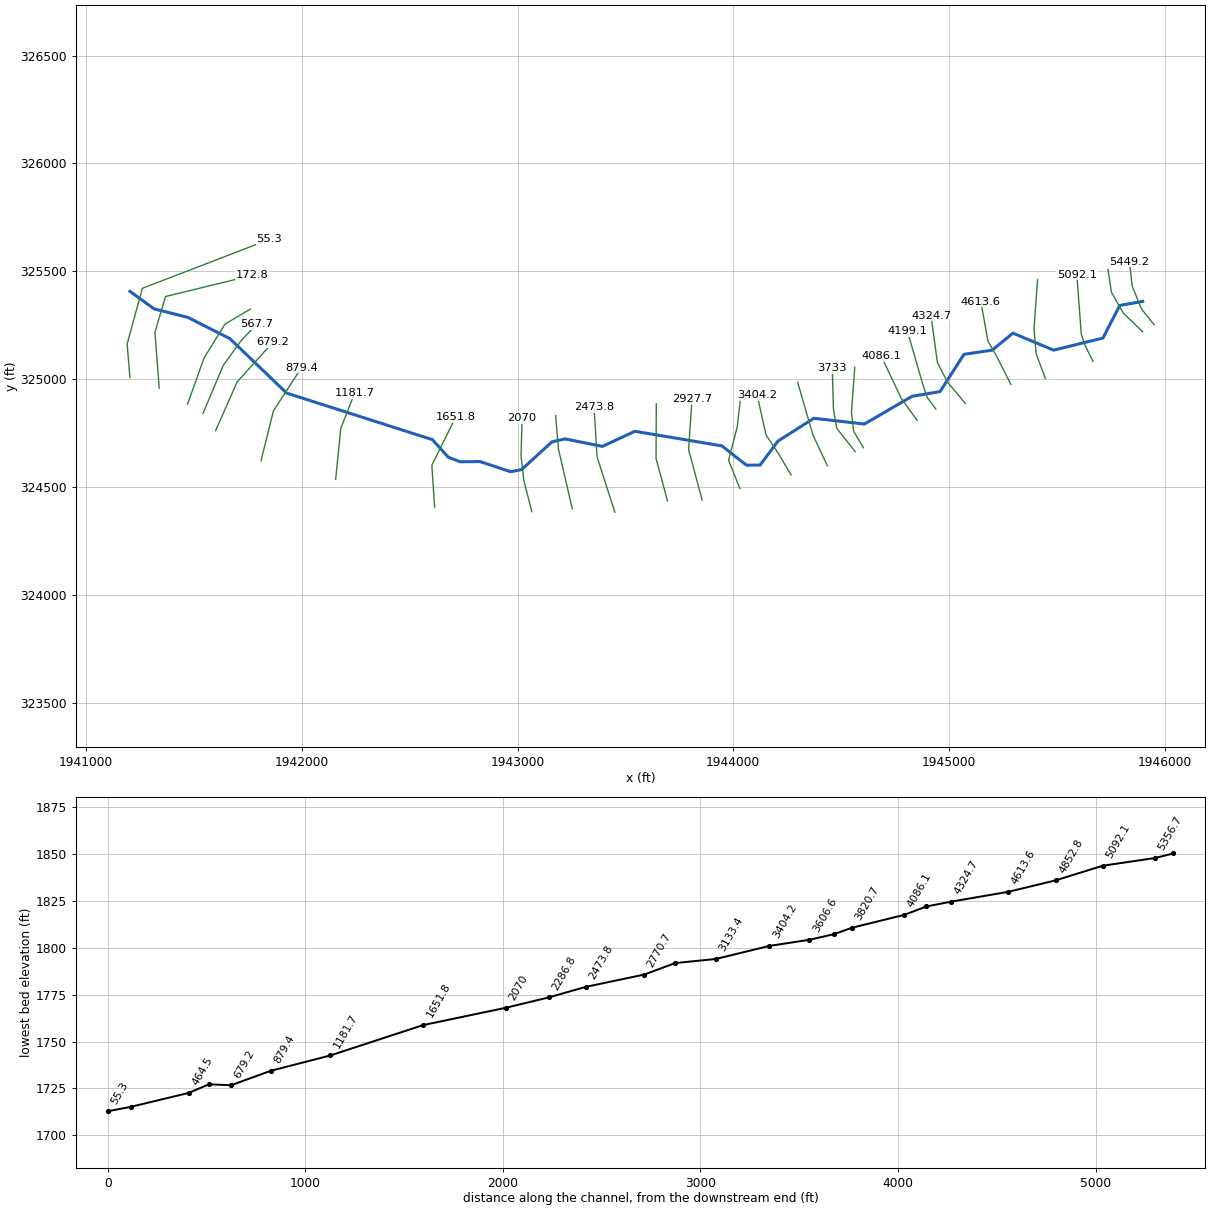
--- BUCKLICKRN.prj (project) ---

Proj Title=BUCKLICKRN
Current Plan=p01
Default Exp/Contr=0,0
English Units
Geom File=g01
Flow File=f01
Plan File=p01
BEGIN DESCRIPTION:
END DESCRIPTION:
DSS Export Rating Curves= 0
DSS Export Rating Curve Sorted= 0
DSS Export Volume Flow Curves= 0
DXF OffsetX= 0
DXF OffsetY= 0
DXF ScaleX= 0
DXF ScaleY= 0

--- BUCKLICKRN.p01 (plan) ---

Plan Title=Floodplain
Program Version=4.00
Geom File=g01
Flow File=f01
K Sum by GR=0
Std Step Tol=0.01
Critical Tol=0.01
Num of Std Step Trials=20
Max Error Tol=0.3
Flow Tol Ratio=0.001
Split Flow NTrial=30
Split Flow Tol=0.02
Split Flow Ratio=0.02
Log Output Level=0
Friction Slope Method=1
Unsteady Friction Slope Method=2
Unsteady Bridges Friction Slope Method=1
Global Log Level=0
CheckData=False
Run HTab=0
Run UNet=0
Run PostProcess=0
UNET Theta=0
UNET Theta Warmup=0
UNET ZTol=0
UNET ZSATol=0
UNET MxIter=0
UNET MaxInSteps=0
UNET DtIC=0
UNET DtMin=0
UNET MaxCRTS=0
UNET WFStab=0
UNET SFStab=0
UNET WFX=0
UNET SFX=0
UNET DSS MLevel=0
UNET DZMax Abort=0
UNET Convert EG Bridges=0
UNET Use Existing IB Tables=0
UNET Froude Limit=0
UNET Froude Power=0
Write IC File=0
Echo Input=False
Echo Output=False
Write Detailed=0

--- BUCKLICKRN.f01 (steady flow) ---

Flow Title=NFF Regression Equation
Program Version=4.00
Number of Profiles=1
Profile Names=P100yr
River Rch & RM=BUCKLICKRN,Main      ,5449.2
517.5811
River Rch & RM=BUCKLICKRN,Main      ,3133.4
568.7079
River Rch & RM=BUCKLICKRN,Main      ,172.8
615.6750
Boundary for River Rch & Prof#=BUCKLICKRN,Main      ,1
Up Type=0
Dn Type=3
Dn Slope=0.036154

--- BUCKLICKRN.g01 (geometry) ---

Geom Title=USGS 10m DEM
Program Version=4.10

River Reach=BUCKLICKRN      ,Main
Reach XY= 30
     1945898.577      325360.403     1945791.964       325341.45
     1945714.192      325190.271     1945485.211       325134.25
     1945296.888      325213.051     1945200.407      325134.112
     1945069.629      325114.719     1944958.735      324941.976
     1944828.518        324920.1     1944608.166      324791.589
     1944373.882      324818.278     1944207.867      324713.026
     1944124.284      324601.238     1944061.379      324600.752
      1943947.45       324690.24     1943544.097      324758.013
     1943393.236      324687.845     1943219.571      324722.929
     1943159.603      324708.773     1943018.631      324580.648
      1942968.37      324570.314     1942825.771      324617.427
     1942733.851      324616.643     1942679.163      324637.477
     1942605.378      324719.074     1941929.163      324935.133
     1941666.135      325187.611     1941472.745      325285.323
     1941314.867       325325.67     1941202.926      325406.646

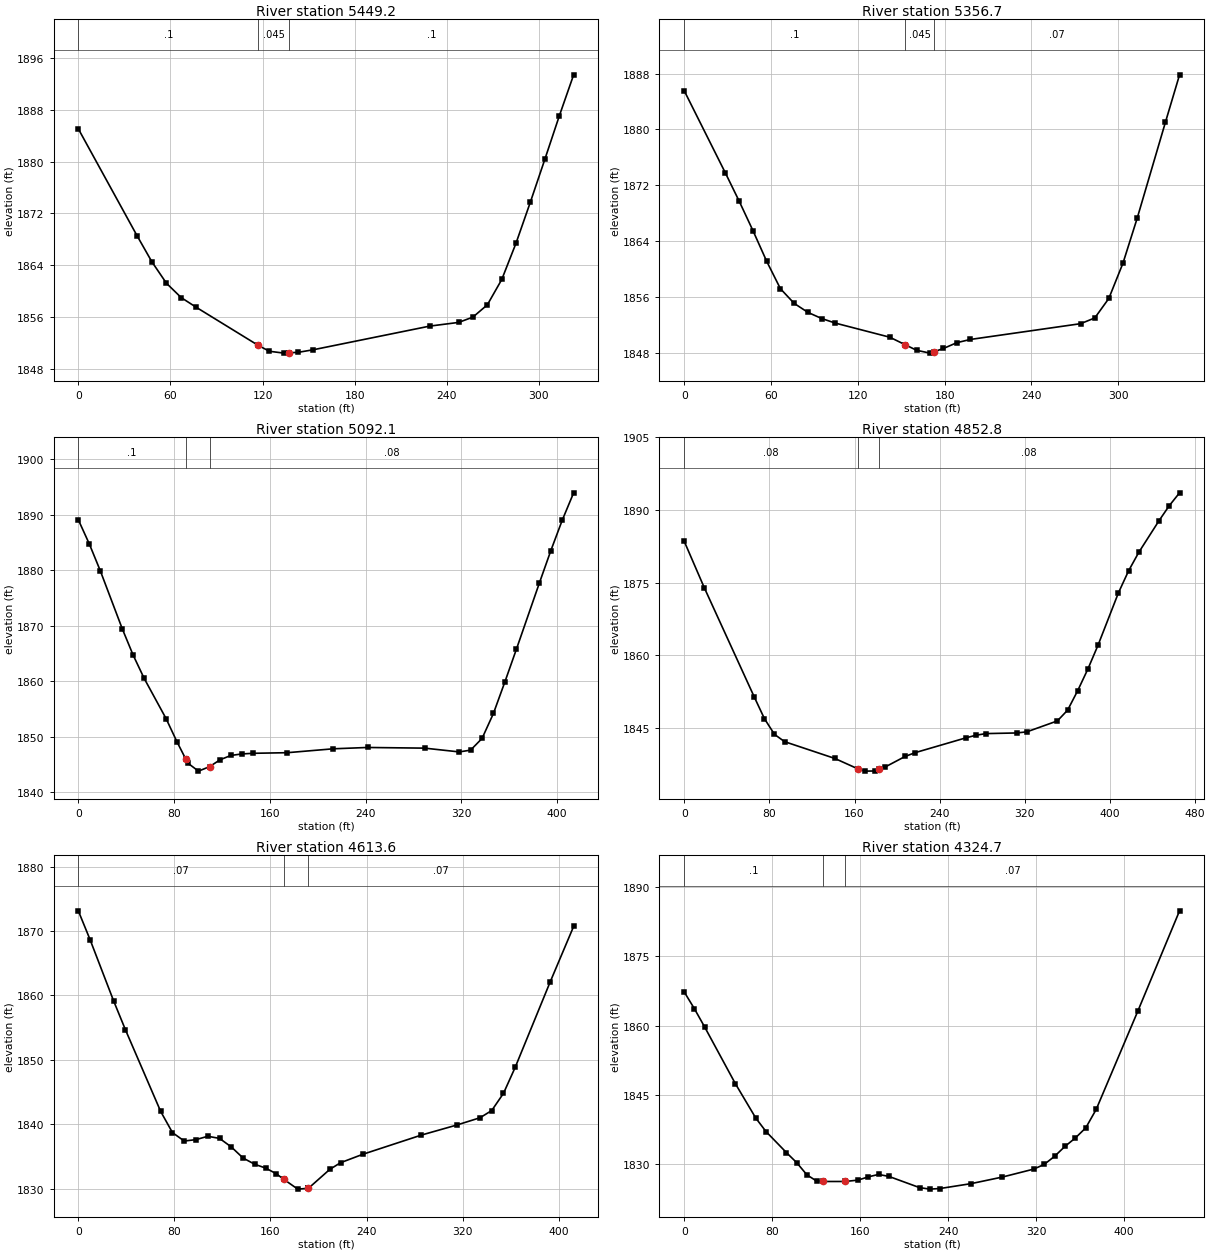
Type RM Length L Ch R = 1 ,5449.2  ,88.7,92.6,95.8
XS GIS Cut Line= 4
     1945951.118       325252.06     1945891.439       325326.93
     1945849.121      325433.266     1945837.185      325545.029
#Sta/Elev= 22
       0 1885.08    38.3 1868.53    47.9 1864.52    57.4  1861.2      67 1858.98
    76.6 1857.51   117.3 1851.57   124.4 1850.68   133.9 1850.39   137.3 1850.44
   143.4 1850.52     153 1850.91   228.9 1854.57   247.7 1855.14     257 1855.96
   266.4 1857.86   275.8 1861.78   285.1 1867.41   294.5  1873.8   303.9  1880.4
   313.2 1887.03   322.6 1893.43
#Mann= 3 , 0 , 0
       0      .1       0   117.3    .045       0   137.3      .1       0
Bank Sta=117.3,137.3
XS Rating Curve= 0 ,0
Exp/Cntr=0.3,0.1

Type RM Length L Ch R = 1 ,5356.7  ,268.2,264.5,258.8
XS GIS Cut Line= 4
     1945897.949      325219.508     1945808.974      325305.228
     1945753.635      325401.799     1945737.359      325508.136
#Sta/Elev= 25
       0 1885.54    28.5 1873.74      38 1869.71    47.5  1865.5      57  1861.1
    66.5 1857.17      76 1855.07    85.5 1853.78      95  1852.9   104.5 1852.24
   142.1 1850.22   152.6 1849.16   160.6 1848.35   169.9 1847.94   172.6 1848.13
   179.2 1848.61   188.5 1849.44   197.8  1849.9     274 1852.16   283.8 1852.98
   293.5 1855.77   303.3 1860.84   313.1 1867.26   332.6    1881   342.4 1887.82
#Mann= 3 , 0 , 0
       0      .1       0   152.6    .045       0   172.6     .07       0
Bank Sta=152.6,172.6
XS Rating Curve= 0 ,0
Exp/Cntr=0.3,0.1

Type RM Length L Ch R = 1 ,5092.1  ,245.1,239.3,233.8
XS GIS Cut Line= 4
     1945667.915      325082.789     1945631.022      325156.574
     1945613.661      325207.572     1945593.045      325484.265
#Sta/Elev= 30
       0 1889.11     9.2 1884.75    18.3 1879.96    36.7 1869.49    45.8 1864.74
      55 1860.55    73.3 1853.31    82.5 1849.09    89.6 1846.08    91.5 1845.28
   100.4 1843.84   109.6 1844.64   118.4 1845.88   127.4 1846.66   136.4 1846.93
   145.9 1847.05   174.6 1847.16   212.9 1847.86   241.6  1848.1   289.4 1847.98
   318.2  1847.3   327.7 1847.62   337.3 1849.73   346.8 1854.23   356.4 1859.93
     366  1865.8   385.1 1877.67   394.7 1883.52   404.3 1889.04   413.8 1893.96
#Mann= 3 , 0 , 0
       0      .1       0    89.6    .045       0   109.6     .08       0
Bank Sta=89.6,109.6
XS Rating Curve= 0 ,0
Exp/Cntr=0.3,0.1

Type RM Length L Ch R = 1 ,4852.8  ,228.7,239.3,250.5
XS GIS Cut Line= 4
      1945446.56      325003.579     1945404.243      325118.596
     1945394.477      325231.444     1945410.753      325460.393
#Sta/Elev= 30
       0 1883.52    18.8 1873.95      66 1851.25    75.4 1846.84    84.8 1843.61
    94.3  1842.1   141.4 1838.64     163  1836.5   169.8 1836.01   179.2 1836.04
     183 1836.36   188.6 1836.84   207.5 1839.04     217 1839.83   264.5 1842.88
   274.1 1843.43   283.6 1843.77   312.3  1843.9   321.9 1844.13   350.6 1846.39
   360.2 1848.61   369.7 1852.64   379.3 1857.13   388.8 1862.04     408 1872.88
   417.5 1877.41   427.1 1881.24   446.2 1887.81   455.8  1890.9   465.4 1893.54
#Mann= 3 , 0 , 0
       0     .08       0     163    .045       0     183     .08       0
Bank Sta=163,183
XS Rating Curve= 0 ,0
Exp/Cntr=0.3,0.1

Type RM Length L Ch R = 1 ,4613.6  ,286.2,288.8,284.1
XS GIS Cut Line= 4
     1945287.055      324975.367     1945220.866      325106.661
     1945180.718      325176.105     1945148.166      325358.397
#Sta/Elev= 30
       0 1873.14     9.8 1868.66    29.4 1859.15    39.2 1854.68    68.6 1841.97
    78.4 1838.69    88.2 1837.38      98  1837.6   107.8 1838.12   117.6 1837.79
   127.4 1836.46   137.2 1834.74     147 1833.76     156 1833.18   164.9 1832.29
   171.1 1831.43   182.7 1829.91   191.1 1830.03   191.6 1830.04   209.4 1832.98
   218.3 1834.01     237 1835.33   285.7 1838.31     315 1839.86   334.5    1841
   344.2 1842.12     354 1844.79   363.7 1848.81   392.9 1862.11   412.4 1870.72
#Mann= 3 , 0 , 0
       0     .07       0   171.1    .045       0   191.1     .07       0
Bank Sta=171.1,191.1
XS Rating Curve= 0 ,0
Exp/Cntr=0.3,0.1

Type RM Length L Ch R = 1 ,4324.7  ,129.4,125.7,124.8
XS GIS Cut Line= 4
     1945076.552      324886.391     1944993.001      324986.218
     1944946.343      325077.364     1944917.046      325293.293
#Sta/Elev= 30
       0 1867.25     9.3 1863.61    18.6 1859.68    46.5 1847.45    65.1 1840.01
    74.4  1837.1      93 1832.55   102.3 1830.39   111.6 1827.75   120.9 1826.34
   126.4 1826.32   146.4 1826.32   158.1 1826.62   167.4 1827.32   176.7 1827.84
     186 1827.43     214    1825   223.3 1824.67   232.6  1824.8     261 1825.86
   289.4 1827.28   317.8 1828.99   327.3 1829.99   336.8 1831.75   346.3  1833.9
   355.7 1835.71   365.2  1837.9   374.7 1841.89   412.6 1863.14   450.5 1884.77
#Mann= 3 , 0 , 0
       0      .1       0   126.4    .045       0   146.4     .07       0
Bank Sta=126.4,146.4
XS Rating Curve= 0 ,0
Exp/Cntr=0.3,0.1

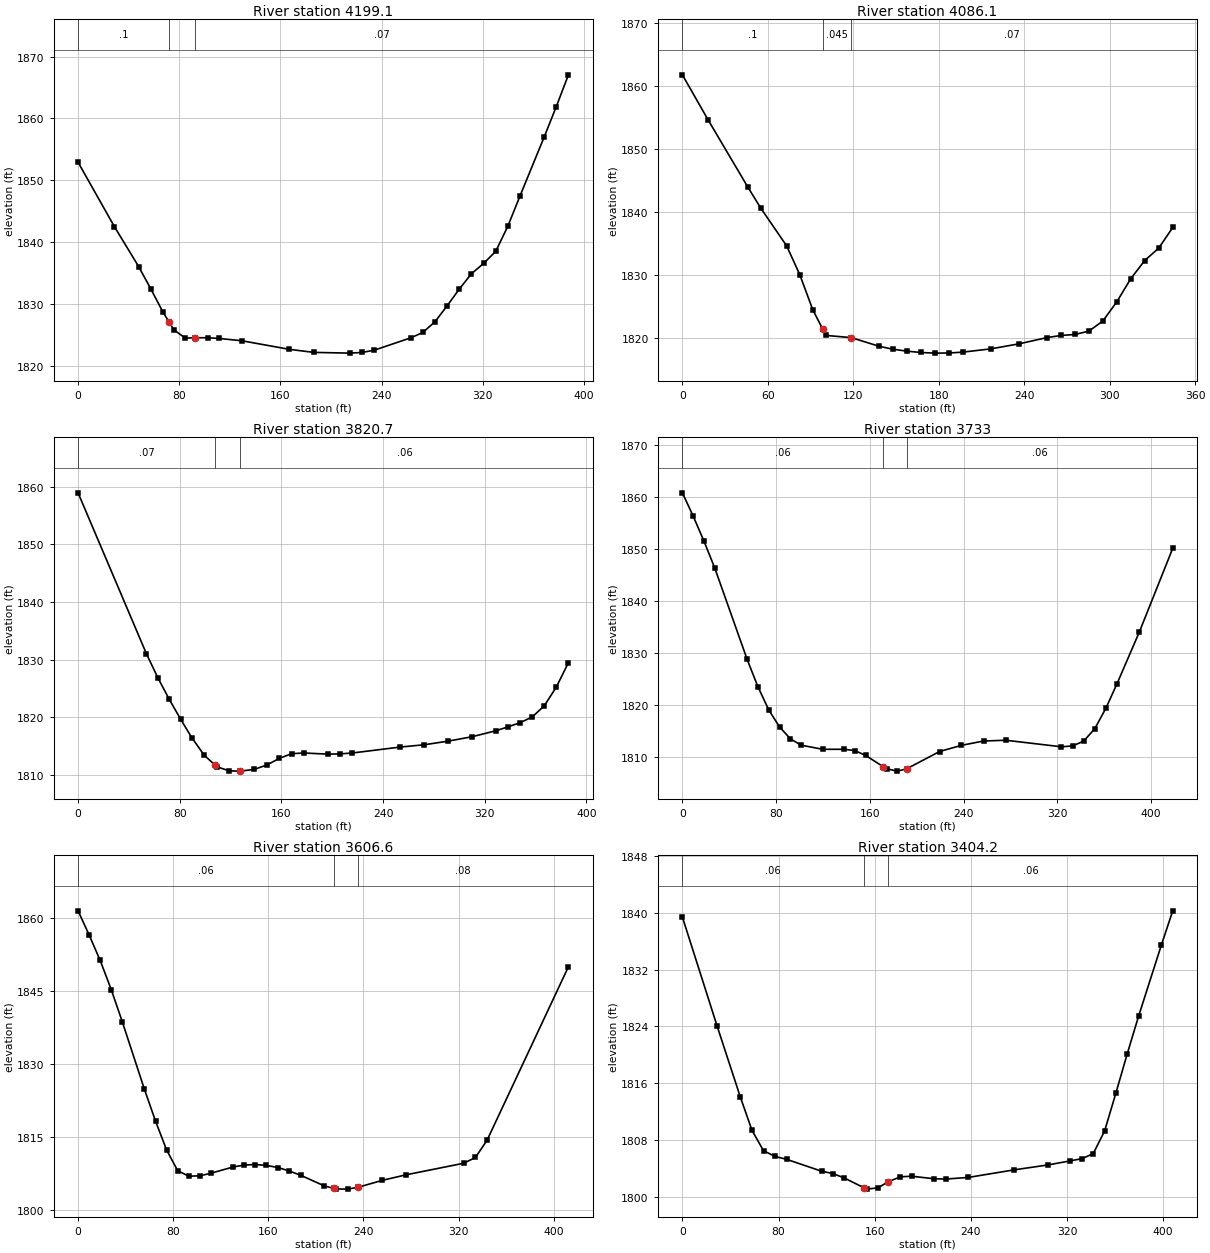
Type RM Length L Ch R = 1 ,4199.1  ,109,113,119.6
XS GIS Cut Line= 4
     1944939.399      324860.784     1944899.468      324914.603
     1944876.899      324982.312     1944807.454      325221.895
#Sta/Elev= 30
       0 1852.92    28.7 1842.53    47.9 1836.07    57.4 1832.51      67 1828.76
    72.2 1827.04    75.9 1825.82    84.9  1824.5    92.2 1824.57   102.7 1824.56
   111.6 1824.45   129.5 1824.08   167.2 1822.69   186.4  1822.2   215.1 1822.08
   224.7 1822.19   234.3 1822.56   263.1 1824.55   272.7 1825.42   282.3 1827.16
   291.9 1829.73   301.5 1832.43   311.1  1834.9   320.7 1836.57   330.3 1838.52
   339.9 1842.59   349.4 1847.42   368.6 1856.98   378.2 1861.91   387.8 1867.04
#Mann= 3 , 0 , 0
       0      .1       0    72.2    .045       0    92.2     .07       0
Bank Sta=72.2,92.2
XS Rating Curve= 0 ,0
Exp/Cntr=0.3,0.1

Type RM Length L Ch R = 1 ,4086.1  ,278,265.4,253.3
XS GIS Cut Line= 3
     1944853.027      324807.724     1944778.158      324911.891
     1944685.927      325107.203
#Sta/Elev= 29
       0 1861.75    18.3 1854.51    45.8    1844      55 1840.61    73.3 1834.58
    82.5    1830    91.6 1824.45    98.6 1821.37   100.8  1820.4   118.6 1820.05
   138.1 1818.68   147.9 1818.21   157.7  1817.9   167.6 1817.69   177.4 1817.59
   187.2 1817.61     197 1817.75   216.6 1818.27   236.3 1819.06   255.9 1820.05
   265.7 1820.39   275.6 1820.55   285.4 1821.08   295.2 1822.68     305 1825.72
   314.8 1829.39   324.6 1832.28   334.5 1834.26   344.3 1837.53
#Mann= 3 , 0 , 0
       0      .1       0    98.6    .045       0   118.6     .07       0
Bank Sta=98.6,118.6
XS Rating Curve= 0 ,0
Exp/Cntr=0.3,0.1

Type RM Length L Ch R = 1 ,3820.7  ,84.5,87.7,89.7
XS GIS Cut Line= 4
     1944603.461      324681.856     1944557.889      324758.896
     1944548.123      324846.786     1944563.314      325054.035
#Sta/Elev= 30
       0 1858.92    53.7 1831.08    62.7 1826.91    71.6  1823.2    80.6 1819.73
    89.5 1816.49    99.3 1813.45   107.6 1811.78   109.2 1811.46     119 1810.74
   127.6  1810.7   138.6    1811   148.5 1811.76   158.3  1812.9   168.1 1813.73
   177.9 1813.84   196.8 1813.64   206.3 1813.69   215.7 1813.84   253.5 1814.87
   272.4 1815.27   291.3  1815.9   310.2 1816.67   329.1 1817.72   338.5 1818.39
     348 1819.11   357.4  1820.1   366.8 1822.02   376.3 1825.27   385.8  1829.5
#Mann= 3 , 0 , 0
       0     .07       0   107.6    .045       0   127.6     .06       0
Bank Sta=107.6,127.6
XS Rating Curve= 0 ,0
Exp/Cntr=0.3,0.1

Type RM Length L Ch R = 1 ,3733    ,125.2,126.4,128.6
XS GIS Cut Line= 4
     1944565.484       324663.41     1944479.764      324771.917
     1944464.573      324860.892     1944459.147      325050.779
#Sta/Elev= 30
       0 1860.88     9.2 1856.41    18.4 1851.61    27.7 1846.38    55.3 1828.83
    64.5 1823.57    73.8  1819.1      83 1815.84    92.2 1813.57   101.4 1812.35
   119.8 1811.56   138.3 1811.56   147.3  1811.3   156.3 1810.39   171.3 1808.23
   174.4 1807.81   183.4 1807.36   191.3 1807.79   219.5 1811.13     238 1812.31
     257 1813.15     276  1813.3   323.5 1812.04     333  1812.2   342.5 1813.13
     352 1815.53   361.5 1819.48     371  1824.2     390 1834.12   418.5 1850.21
#Mann= 3 , 0 , 0
       0     .06       0   171.3    .045       0   191.3     .06       0
Bank Sta=171.3,191.3
XS Rating Curve= 0 ,0
Exp/Cntr=0.3,0.1

Type RM Length L Ch R = 1 ,3606.6  ,194.4,202.4,210.1
XS GIS Cut Line= 3
     1944436.361      324598.306     1944369.086      324741.535
     1944298.557      324985.675
#Sta/Elev= 30
       0 1861.47     9.3 1856.52    18.6 1851.28    27.9  1845.3    37.2 1838.69
    55.8 1824.83    65.2 1818.25    74.5 1812.35    83.8  1808.1    93.1 1806.98
   102.4 1807.05   111.7 1807.58   130.3 1808.86   139.6 1809.27   148.9 1809.37
   158.2  1809.2     168 1808.76   177.8 1808.04   187.6 1807.12   207.1 1804.98
   215.3 1804.45   216.9 1804.35   226.7 1804.32   235.3 1804.69     256 1806.13
   275.5 1807.24   324.4 1809.64   334.2 1810.82     344 1814.37   412.4 1849.99
#Mann= 3 , 0 , 0
       0     .06       0   215.3    .045       0   235.3     .08       0
Bank Sta=215.3,235.3
XS Rating Curve= 0 ,0
Exp/Cntr=0.3,0.1

Type RM Length L Ch R = 1 ,3404.2  ,291.7,270.8,250.2
XS GIS Cut Line= 4
     1944268.175      324554.903     1944209.581      324654.729
     1944152.073       324740.45      1944110.84      324924.911
#Sta/Elev= 30
       0 1839.45    28.9 1824.06    48.2 1814.06    57.9 1809.36    67.5 1806.47
    77.2 1805.66    86.8 1805.25   115.8 1803.58   125.1 1803.25   134.5 1802.64
     151 1801.25   153.3 1801.05   162.7 1801.23     171 1802.07   181.4 1802.79
   190.8 1802.87   209.6 1802.51     219 1802.47   237.9  1802.7   275.7 1803.76
     304 1804.46   322.9 1805.04   332.4 1805.35   341.8 1806.05   351.3 1809.25
   360.7  1814.6   370.2 1820.18   379.6 1825.46   398.5 1835.47     408 1840.32
#Mann= 3 , 0 , 0
       0     .06       0     151    .045       0     171     .06       0
Bank Sta=151,171
XS Rating Curve= 0 ,0
Exp/Cntr=0.3,0.1

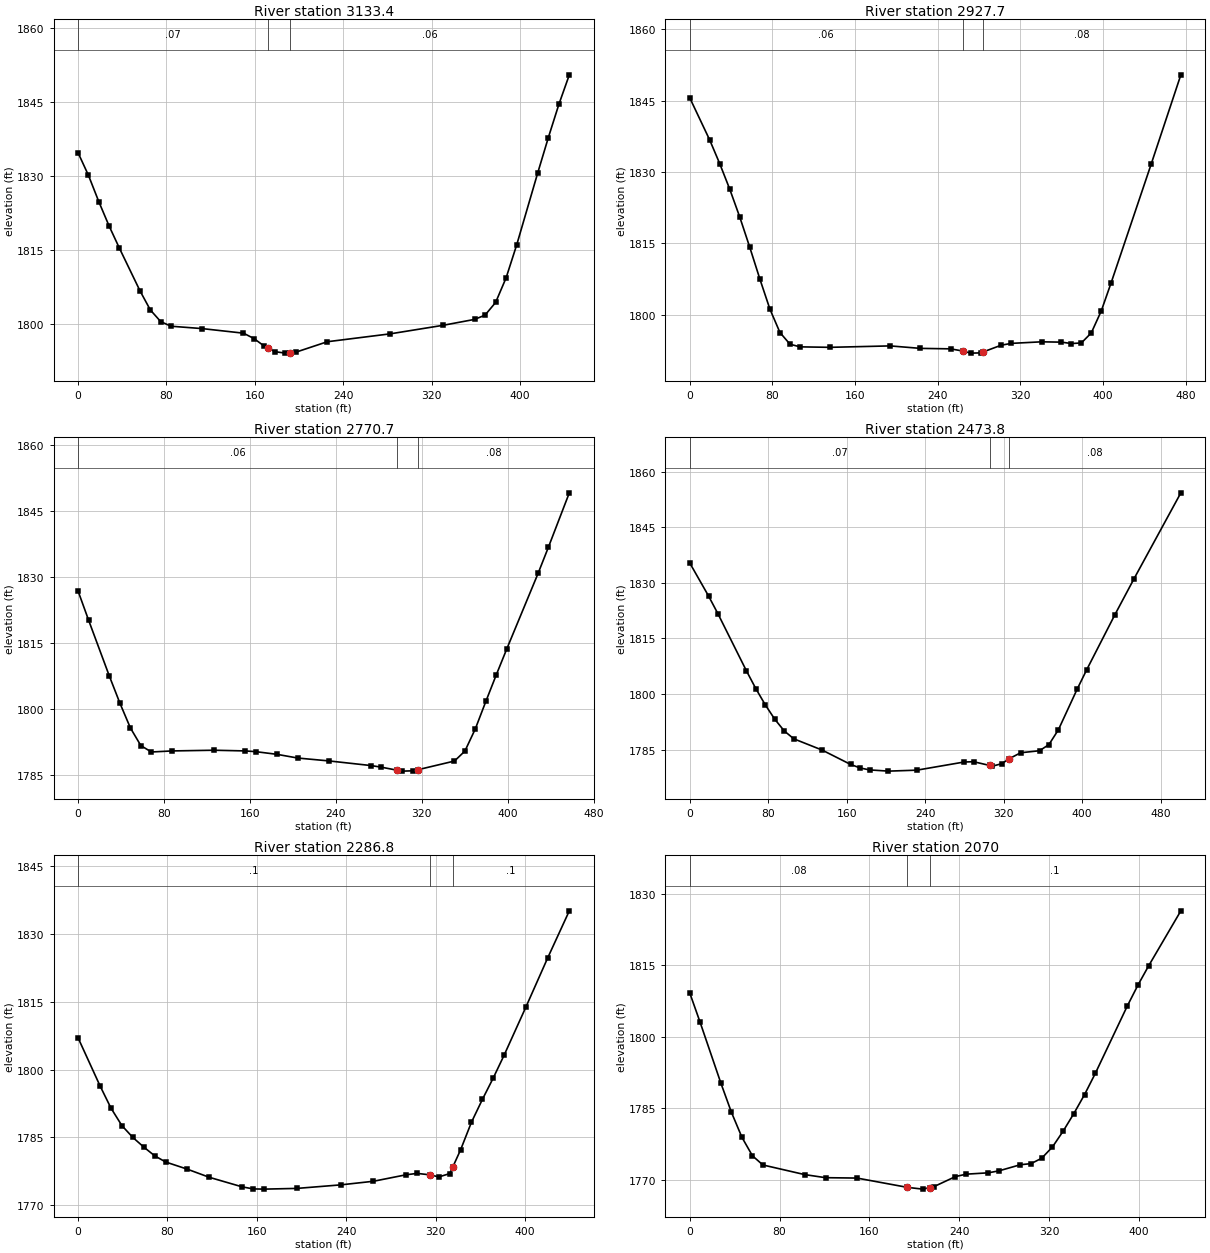
Type RM Length L Ch R = 1 ,3133.4  ,200.8,205.7,208.8
XS GIS Cut Line= 4
     1944030.545      324493.054     1943978.461      324623.262
     1944018.609      324779.512     1944034.885      324921.656
#Sta/Elev= 30
       0 1834.66     9.4 1830.09    18.7 1824.79      28 1819.87    37.4 1815.34
    56.1 1806.67    65.4 1802.83    74.8 1800.47    84.1 1799.54   112.2 1799.06
   149.7 1798.13   159.2 1797.04   168.7 1795.47   171.5 1795.15   178.2 1794.38
   187.7 1794.09   191.5 1794.17   197.2 1794.29   225.6  1796.4   282.6    1798
   330.2 1799.72   358.8 1800.92   368.3 1801.78   377.9 1804.36   387.4 1809.35
     397 1816.04     416 1830.59   425.6 1837.74   435.1 1844.45   444.6 1850.46
#Mann= 3 , 0 , 0
       0     .07       0   171.5    .045       0   191.5     .06       0
Bank Sta=171.5,191.5
XS Rating Curve= 0 ,0
Exp/Cntr=0.3,0.1

Type RM Length L Ch R = 1 ,2927.7  ,156,157,158.7
XS GIS Cut Line= 4
     1943855.849        324438.8     1943792.915      324673.175
     1943799.425      324770.832     1943809.191       324905.38
#Sta/Elev= 30
       0 1845.67    19.4 1836.76    29.1 1831.78    38.8 1826.41    48.5 1820.54
    58.2 1814.17      68 1807.47    77.7 1801.15    87.4 1796.24    97.1 1793.78
   106.8 1793.22   135.9 1793.12   194.1 1793.42   223.3  1792.9   252.5  1792.8
   264.2 1792.35     272  1791.9   281.8 1791.95   284.2 1792.16   301.4 1793.56
   311.2 1793.95   340.6 1794.28   359.8 1794.21   369.5 1793.92   379.1 1794.04
   388.7 1796.15   398.4 1800.79     408 1806.75   446.6 1831.62   475.4 1850.46
#Mann= 3 , 0 , 0
       0     .06       0   264.2    .045       0   284.2     .08       0
Bank Sta=264.2,284.2
XS Rating Curve= 0 ,0
Exp/Cntr=0.3,0.1

Type RM Length L Ch R = 1 ,2770.7  ,294.8,296.8,298.4
XS GIS Cut Line= 3
     1943695.258       324434.46      1943642.09      324631.943
     1943643.175      324884.764
#Sta/Elev= 29
       0 1826.77     9.7  1820.2    29.2 1807.35      39  1801.2    48.7  1795.6
    58.4 1791.59    68.2 1790.13    87.6 1790.37   126.6 1790.53   155.8 1790.37
   165.6  1790.2     185  1789.6   204.5 1788.75   233.7 1788.09   272.6 1787.04
   282.3 1786.67   296.5    1786   301.8 1785.77   311.5 1785.84   316.5  1786.1
   350.4 1788.07   360.1 1790.34   369.8  1795.4   379.6 1801.66   389.3  1807.7
     399 1813.56   428.2  1830.8   437.9 1836.82   457.3 1849.16
#Mann= 3 , 0 , 0
       0     .06       0   296.5    .045       0   316.5     .08       0
Bank Sta=296.5,316.5
XS Rating Curve= 0 ,0
Exp/Cntr=0.3,0.1

Type RM Length L Ch R = 1 ,2473.8  ,186.6,187.1,187.8
XS GIS Cut Line= 3
     1943451.118      324382.377     1943368.652      324639.538
     1943354.546      324869.573
#Sta/Elev= 30
       0  1835.4    19.3 1826.42    28.9 1821.61    57.9 1806.22    67.5 1801.41
    77.2 1797.01    86.8 1793.16    96.4 1790.03   106.1  1787.9     135 1784.86
     164 1780.99   173.6 1780.04   183.3 1779.51   202.6 1779.18   231.5 1779.44
   279.7 1781.64   289.3 1781.72   305.6 1780.72   308.5 1780.52   318.1 1781.19
   325.6 1782.53   337.3 1784.14   356.5 1784.68   366.1 1786.35   375.7 1790.33
   394.9 1801.33   404.5  1806.5   433.3 1821.39   452.5 1830.95   500.5 1854.27
#Mann= 3 , 0 , 0
       0     .07       0   305.6    .045       0   325.6     .08       0
Bank Sta=305.6,325.6
XS Rating Curve= 0 ,0
Exp/Cntr=0.3,0.1

Type RM Length L Ch R = 1 ,2286.8  ,216.8,216.8,214.6
XS GIS Cut Line= 3
     1943253.635      324398.653     1943189.616      324675.345
     1943176.595       324830.51
#Sta/Elev= 30
       0 1807.01    19.6 1796.42    29.4 1791.49    39.2 1787.61      49 1784.99
    58.8 1782.86    68.6 1780.92    78.4 1779.56    97.9 1777.96   117.5 1776.17
   146.9 1774.06   156.7 1773.61   166.5 1773.56   195.9 1773.72     235  1774.5
   264.4  1775.3   293.7 1776.74   303.5 1777.04   315.3 1776.71   322.9 1776.26
   332.7    1777   335.3 1778.41   342.4 1782.27   352.1 1788.36   361.9 1793.41
   371.6 1798.14   381.3 1803.17   400.8 1813.82   420.2 1824.63   439.7 1835.12
#Mann= 3 , 0 , 0
       0      .1       0   315.3    .045       0   335.3      .1       0
Bank Sta=315.3,335.3
XS Rating Curve= 0 ,0
Exp/Cntr=0.3,0.1

Type RM Length L Ch R = 1 ,2070    ,430.9,418.2,405.9
XS GIS Cut Line= 4
     1943065.918      324385.632     1943029.026      324529.946
     1943016.005      324646.049      1943021.43       324817.49
#Sta/Elev= 30
       0 1809.28     9.3 1803.07    27.9 1790.23    37.2 1784.17    46.6  1778.9
    55.9 1775.05    65.2 1773.12   102.4  1771.1     121 1770.45     149 1770.37
   193.6 1768.43   207.4 1768.05   213.6 1768.36   217.1 1768.53   236.6 1770.68
   246.3 1771.19   265.8 1771.47   275.3 1771.88   294.4 1773.17   303.9  1773.4
   313.4 1774.53     323  1776.9   332.5 1780.21     342 1783.89   351.6  1787.9
   361.1 1792.31   389.7 1806.51   399.2  1810.9   408.7 1814.93   437.3 1826.44
#Mann= 3 , 0 , 0
       0     .08       0   193.6    .045       0   213.6      .1       0
Bank Sta=193.6,213.6
XS Rating Curve= 0 ,0
Exp/Cntr=0.3,0.1

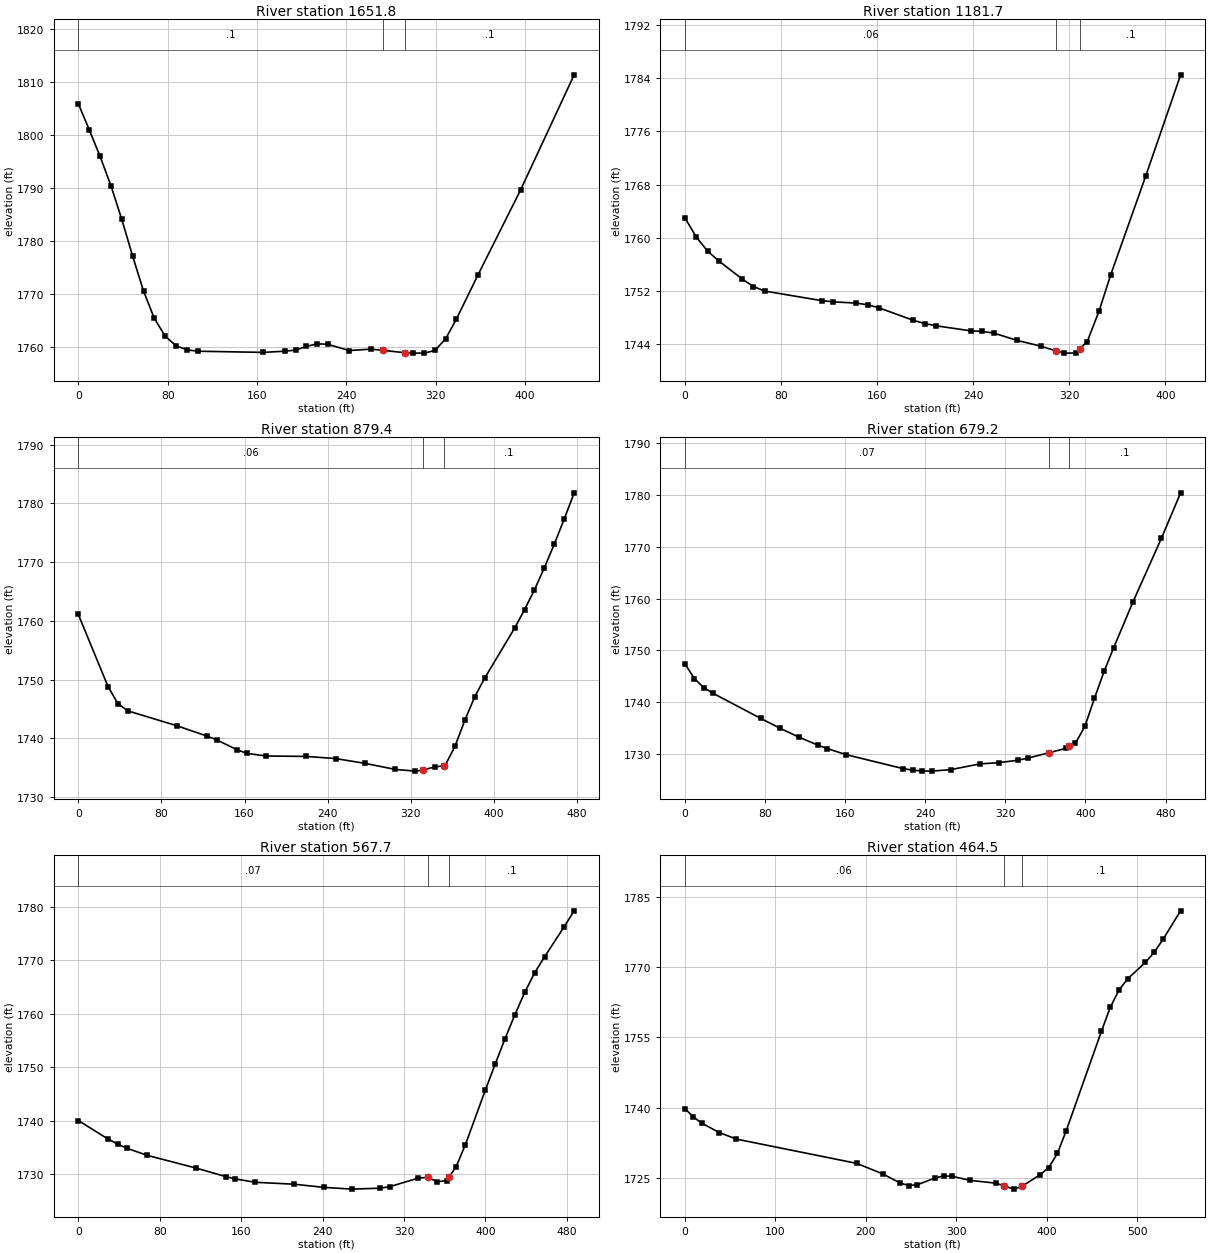
Type RM Length L Ch R = 1 ,1651.8  ,468.1,470,471.9
XS GIS Cut Line= 3
     1942615.614      324406.248     1942602.593      324600.476
      1942713.27         324824.
#Sta/Elev= 30
       0 1805.94     9.7 1801.06    19.5 1795.98    29.2 1790.45    38.9  1784.1
    48.7 1777.12    58.4 1770.53    68.1 1765.37    77.9 1761.99    87.6 1760.21
    97.3 1759.44   107.1 1759.18   165.5 1758.96   184.9 1759.18   194.7  1759.4
   204.3 1760.09   213.8 1760.58   223.4 1760.49   242.6 1759.31   261.8 1759.57
   272.5 1759.35   292.5  1758.9   300.2 1758.82   309.8 1758.82   319.4 1759.33
     329 1761.53   338.6 1765.24   357.8 1773.53   396.1 1789.64   444.1  1811.4
#Mann= 3 , 0 , 0
       0      .1       0   272.5    .045       0   292.5      .1       0
Bank Sta=272.5,292.5
XS Rating Curve= 0 ,0
Exp/Cntr=0.3,0.1

Type RM Length L Ch R = 1 ,1181.7  ,307.4,302.3,297.2
XS GIS Cut Line= 3
      1942156.63      324535.371     1942180.501      324771.917
      1942244.52      324934.677
#Sta/Elev= 29
       0 1763.02     9.5 1760.11      19 1757.97    28.5 1756.47    47.6  1753.8
    57.1 1752.64    66.6 1751.96   114.1 1750.52   123.6 1750.34   142.6 1750.15
   152.2  1749.9   161.7 1749.43   190.2 1747.56   199.7 1747.07   209.2 1746.73
   237.8 1745.98   247.5 1745.89   257.2 1745.63   276.6 1744.53     296 1743.68
   308.9 1742.95   315.5 1742.62   325.2 1742.63   328.9 1743.29   334.9 1744.36
   344.6 1748.89   354.4  1754.4   383.5 1769.25   412.6 1784.52
#Mann= 3 , 0 , 0
       0     .06       0   308.9    .045       0   328.9      .1       0
Bank Sta=308.9,328.9
XS Rating Curve= 0 ,0
Exp/Cntr=0.3,0.1

Type RM Length L Ch R = 1 ,879.4   ,204,200.2,196.1
XS GIS Cut Line= 3
     1941810.493      324621.092     1941868.001      324852.212
      1941998.21       325052.95
#Sta/Elev= 30
       0 1761.07    28.6  1748.8    38.1  1745.9    47.6 1744.67    95.3 1742.11
   123.8 1740.38   133.4 1739.72   152.4 1738.08     162 1737.44     181 1736.98
   219.1 1736.92   247.7 1736.55   276.4 1735.72   305.2  1734.7   324.3 1734.41
   331.9 1734.59   343.4 1735.15   351.9  1735.3     353 1735.32   362.6 1738.62
   372.2 1743.09   381.7 1747.07   391.3 1750.26     420 1758.73   429.6 1761.88
   439.2 1765.28   448.7 1769.04   458.3 1773.06   467.9 1777.35   477.4 1781.78
#Mann= 3 , 0 , 0
       0     .06       0   331.9    .045       0   351.9      .1       0
Bank Sta=331.9,351.9
XS Rating Curve= 0 ,0
Exp/Cntr=0.3,0.1

Type RM Length L Ch R = 1 ,679.2   ,108.9,111.5,114.2
XS GIS Cut Line= 3
     1941599.989      324761.066     1941699.816       324986.76
     1941865.831      325171.222
#Sta/Elev= 30
       0 1747.47     9.5 1744.58      19  1742.8    28.5  1741.7    75.9 1736.88
    94.9 1735.01   113.9 1733.28   132.9 1731.74   142.4 1731.06   161.4 1729.89
   218.3  1727.2   227.8 1726.91   237.3 1726.76   246.8 1726.73   265.9 1727.03
   294.5 1728.12   313.6 1728.36   332.7 1728.84   342.2 1729.22   363.9 1730.29
   380.4 1731.12   383.9 1731.48     390 1732.11   399.5  1735.4     409 1740.79
   418.6 1745.95   428.1 1750.49   447.2 1759.24   475.9 1771.65     495 1780.37
#Mann= 3 , 0 , 0
       0     .07       0   363.9    .045       0   383.9      .1       0
Bank Sta=363.9,383.9
XS Rating Curve= 0 ,0
Exp/Cntr=0.3,0.1

Type RM Length L Ch R = 1 ,567.7   ,101.5,103.3,105
XS GIS Cut Line= 4
     1941541.829      324841.687     1941635.579      325063.909
     1941717.177      325176.756     1941790.093      325254.881
#Sta/Elev= 30
       0 1740.07    28.9 1736.64    38.6 1735.66    48.2 1734.85    67.5 1733.57
   115.8 1731.17   144.7  1729.6   154.4 1729.15   173.7 1728.52   212.2 1728.16
   241.2 1727.57     269 1727.24   296.9 1727.42   306.2 1727.71     334 1729.29
   343.3 1729.45   352.6 1728.62   361.9 1728.84   364.5 1729.55   371.2 1731.39
   380.4 1735.55   399.9  1745.7   409.6 1750.59   419.3 1755.33     429 1759.82
   438.7 1764.02   448.4 1767.68   458.2 1770.67   477.6 1776.34   487.3 1779.28
#Mann= 3 , 0 , 0
       0     .07       0   343.3    .045       0   364.5      .1       0
Bank Sta=343.3,364.5
XS Rating Curve= 0 ,0
Exp/Cntr=0.3,0.1

Type RM Length L Ch R = 1 ,464.5   ,284.6,291.6,298.4
XS GIS Cut Line= 4
     1941469.781      324883.679     1941546.821      325098.523
     1941643.392      325254.773     1941760.579      325324.217
#Sta/Elev= 30
       0 1739.83     9.5 1738.02      19 1736.68      38 1734.71    57.1  1733.3
   190.2 1728.11   218.7 1725.88   237.9 1723.94   247.6 1723.38   257.2 1723.57
   276.6    1725   286.2 1725.46   295.9 1725.34   315.2  1724.5   344.2 1723.88
   352.5 1723.34   363.6 1722.62   372.5 1723.19   392.6 1725.67   402.3 1727.22
   411.9 1730.24   421.6 1735.08   460.6 1756.34   470.3 1761.42     480 1765.14
   489.8 1767.57   509.2 1771.03     519 1773.21   528.7 1775.97   548.1 1782.04
#Mann= 3 , 0 , 0
       0     .06       0   352.5    .045       0   372.5      .1       0
Bank Sta=352.5,372.5
XS Rating Curve= 0 ,0
Exp/Cntr=0.3,0.1

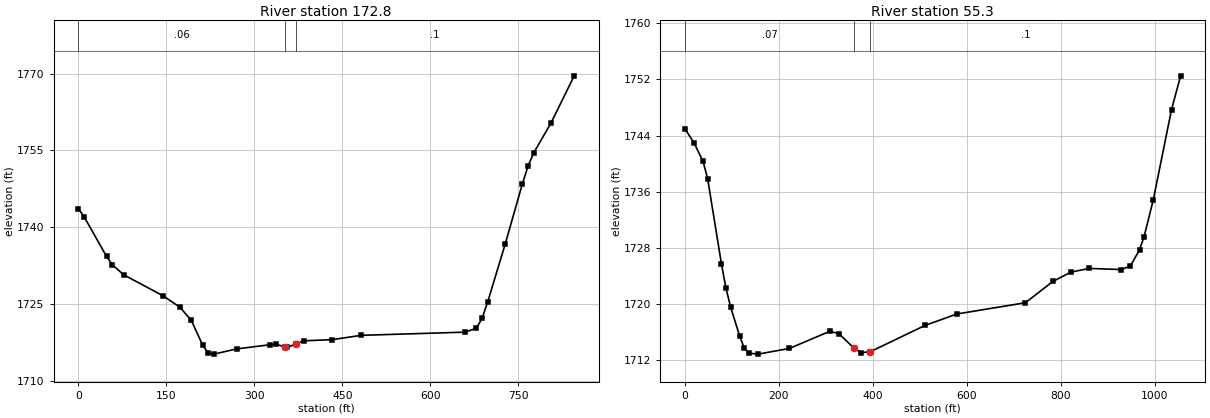
Type RM Length L Ch R = 1 ,172.8   ,116.8,117.6,118.5
XS GIS Cut Line= 4
     1941338.487      324957.464     1941318.956      325216.795
     1941367.784      325382.811     1941768.175      325480.467
#Sta/Elev= 30
       0 1743.66     9.6  1742.1    48.2  1734.3    57.8 1732.71    77.1 1730.74
   144.5 1726.62   173.4 1724.38   192.6 1721.81   211.9 1717.01   221.5 1715.41
   231.2 1715.24   269.7 1716.26   327.4 1717.08     337 1717.15   351.6 1716.69
   356.2 1716.54   371.6 1717.29     385 1717.84   433.1 1718.07   482.2 1718.91
   658.8 1719.53   678.4 1720.27   688.2 1722.21     698  1725.5   727.5 1736.67
   756.9 1748.47   766.7 1751.99   776.6  1754.6     806 1760.42   845.2 1769.57
#Mann= 3 , 0 , 0
       0     .06       0   351.6    .045       0   371.6      .1       0
Bank Sta=351.6,371.6
XS Rating Curve= 0 ,0
Exp/Cntr=0.3,0.1

Type RM Length L Ch R = 1 ,55.3    ,64.6,55.3,45.8
XS GIS Cut Line= 4
     1941202.854      325007.377     1941189.833      325162.542
     1941260.362      325420.788     1941849.555      325647.568
#Sta/Elev= 30
       0    1745    19.5 1742.99    38.9 1740.32    48.7 1737.82    77.9 1725.74
    87.6 1722.26    97.3 1719.62   116.8 1715.42   126.5 1713.71   136.2 1713.01
   155.7 1712.87   222.6 1713.68   308.7 1716.13   327.8 1715.78   360.5 1713.69
   375.6 1713.08   394.7 1713.22   510.8 1716.95   578.8 1718.59   724.5 1720.19
   782.8 1723.22   821.6 1724.56   860.5 1725.08   928.5 1724.92   947.9 1725.43
   967.3 1727.73     977 1729.61   996.5 1734.83  1035.3  1747.7  1054.7 1752.52
#Mann= 3 , 0 , 0
       0     .07       0   360.5    .045       0   394.7      .1       0
Bank Sta=360.5,394.7
XS Rating Curve= 0 ,0
Exp/Cntr=0.3,0.1

Chan Stop Cuts=-1
Use User Specified Reach Order=0
Composite Channel Slope=5